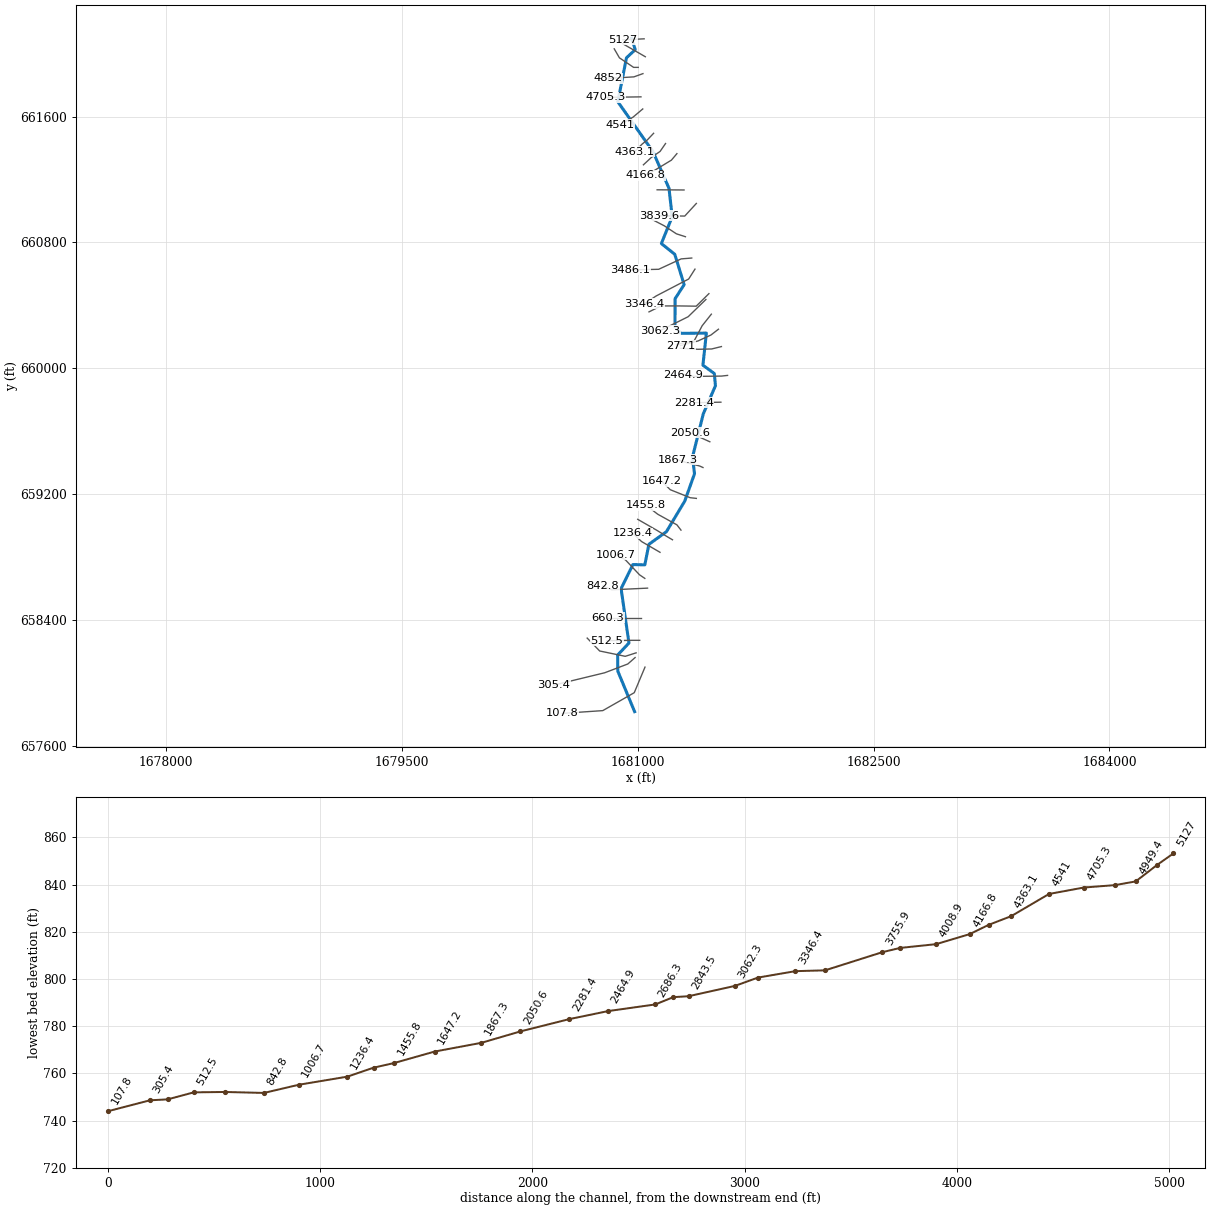
--- PRMRRN.prj (project) ---

Proj Title=PRMRRN
Current Plan=p01
Default Exp/Contr=0,0
English Units
Geom File=g01
Flow File=f01
Plan File=p01
BEGIN DESCRIPTION:
END DESCRIPTION:
DSS Export Rating Curves= 0
DSS Export Rating Curve Sorted= 0
DSS Export Volume Flow Curves= 0
DXF Filename=..\..\..\..\..\Engineering\Hydraulics\PRMRRN\PRMRRN.
DXF OffsetX= 0
DXF OffsetY= 0
DXF ScaleX= 0
DXF ScaleY= 0

--- PRMRRN.p01 (plan) ---

Plan Title=Floodplain
Program Version=4.00
Geom File=g01
Flow File=f01
K Sum by GR=0
Std Step Tol=0.01
Critical Tol=0.01
Num of Std Step Trials=20
Max Error Tol=0.3
Flow Tol Ratio=0.001
Split Flow NTrial=30
Split Flow Tol=0.02
Split Flow Ratio=0.02
Log Output Level=0
Friction Slope Method=1
Unsteady Friction Slope Method=2
Unsteady Bridges Friction Slope Method=1
Global Log Level=0
CheckData=False
Run HTab=0
Run UNet=0
Run PostProcess=0
UNET Theta=0
UNET Theta Warmup=0
UNET ZTol=0
UNET ZSATol=0
UNET MxIter=0
UNET MaxInSteps=0
UNET DtIC=0
UNET DtMin=0
UNET MaxCRTS=0
UNET WFStab=0
UNET SFStab=0
UNET WFX=0
UNET SFX=0
UNET DSS MLevel=0
UNET DZMax Abort=0
UNET Convert EG Bridges=0
UNET Use Existing IB Tables=0
UNET Froude Limit=0
UNET Froude Power=0
Write IC File=0
Echo Input=False
Echo Output=False
Write Detailed=0

--- PRMRRN.f01 (steady flow) ---

Flow Title=NFF Regression Equation
Program Version=4.00
Number of Profiles=1
Profile Names=P100yr
River Rch & RM=PRMRRN,Main      ,5127
905.9322
River Rch & RM=PRMRRN,Main      ,3839.6
964.1183
River Rch & RM=PRMRRN,Main      ,842.8
1028.133
Boundary for River Rch & Prof#=PRMRRN,Main      ,1
Up Type=0
Dn Type=3
Dn Slope=0.0168

--- PRMRRN.g01 (geometry) ---

Geom Title=2003 WVU SAMB 3 Meter DEM
Program Version=4.10

River Reach=PRMRRN          ,Main
Reach XY= 30
     1680961.006      662098.269      1680983.43      662026.009
     1680927.658      661974.576     1680872.734      661694.592
     1681096.432      661377.404     1681198.081      661144.505
      1681218.35      660963.407       1681149.6      660792.921
     1681234.756      660724.778     1681294.392      660531.549
     1681236.623      660441.575     1681236.319      660263.255
     1681273.558      660221.762     1681435.798      660223.411
     1681413.923      660019.244     1681486.579      659966.119
      1681493.61      659888.515     1681416.267      659709.696
     1681347.864      659435.598     1681360.364      659328.307
     1681298.124      659154.349     1681181.822      658960.172
     1681070.346      658880.043     1681044.305       658749.14
     1680968.568      658751.141     1680893.469      658597.988
     1680943.396      658252.043     1680871.475      658175.486
      1680872.56      658073.055     1680979.244      657815.612

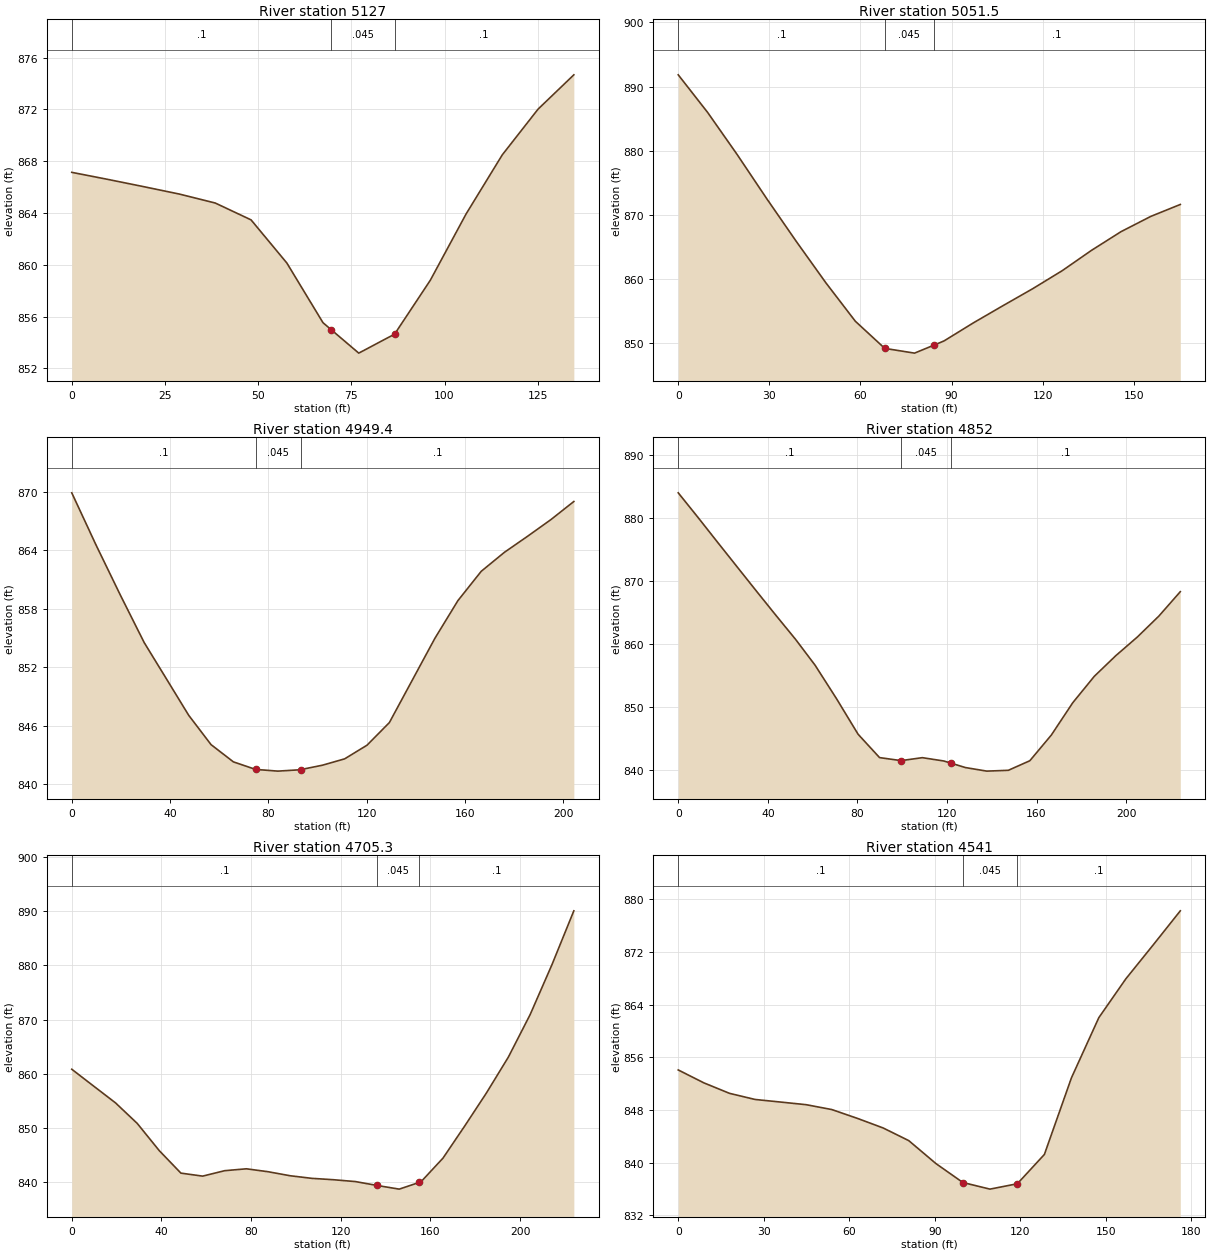
Type RM Length L Ch R = 1 ,5127    ,88.8,75.5,60
XS GIS Cut Line= 2
     1681040.058       662095.13     1680905.509       662088.62
#Sta/Elev= 17
       0  867.14     9.6   866.6    19.2  866.04    28.9  865.46    38.5  864.77
    48.1  863.47    57.7  860.14    67.4  855.53    69.6  854.99      77  853.18
    84.6  854.34    86.6  854.64    96.2  858.81   105.8  863.93   115.5  868.49
   125.1  872.02   134.7  874.67
#Mann= 3 , 0 , 0
       0      .1       0    69.6    .045       0    86.6      .1       0
Bank Sta=69.6,86.6
XS Rating Curve= 0 ,0
Exp/Cntr=0.3,0.1

Type RM Length L Ch R = 1 ,5051.5  ,108,102.2,98.9
XS GIS Cut Line= 2
     1681047.653      661981.198     1680904.424      662063.663
#Sta/Elev= 20
       0  891.83     9.7  885.95    19.4  879.39    29.2  872.46    38.9  865.81
    48.6  859.38    58.3  853.38      68  849.14    69.2  849.05    77.8   848.4
    84.2  849.65    87.5   850.3    97.2  853.13   106.9   855.8   116.7  858.45
   126.4  861.26   136.1  864.45   145.8  867.36   155.6  869.74   165.3   871.6
#Mann= 3 , 0 , 0
       0      .1       0      68    .045       0    84.2      .1       0
Bank Sta=68,84.2
XS Rating Curve= 0 ,0
Exp/Cntr=0.3,0.1

Type RM Length L Ch R = 1 ,4949.4  ,76.5,97.4,115
XS GIS Cut Line= 4
     1681002.514      661913.576        1680973.      661913.576
     1680882.723       661974.34     1680849.737      662031.632
#Sta/Elev= 25
       0  869.87     9.8  864.56    19.7  859.42    29.5   854.5    38.6  850.76
    47.6  847.05    56.7  844.04    65.8  842.27    74.9  841.49    78.3  841.43
    83.9  841.32      93  841.46    93.3  841.48   102.1  841.93   111.1  842.58
   120.2  843.98   129.3   846.3   138.3   850.5   147.8  854.93   157.2  858.81
   166.7  861.82   176.1  863.76   185.6  865.42     195  867.11   204.4  868.98
#Mann= 3 , 0 , 0
       0      .1       0    74.9    .045       0    93.3      .1       0
Bank Sta=74.9,93.3
XS Rating Curve= 0 ,0
Exp/Cntr=0.3,0.1

Type RM Length L Ch R = 1 ,4852    ,147.4,146.7,141.5
XS GIS Cut Line= 3
     1681032.462      661873.776     1680974.954      661853.159
     1680812.193      661843.394
#Sta/Elev= 27
       0  883.98     8.7  880.13    17.4   876.2    26.2  872.26    34.9  868.37
    43.6  864.52    52.4  860.69    61.1  856.59    70.7  851.25    80.3  845.62
    89.9   841.9    99.5  841.42   106.6  841.77     109  841.89   118.6  841.36
   121.6  841.04   128.2  840.32   137.8  839.75   147.4  839.88     157   841.4
   166.6  845.48   176.2  850.63   185.8  854.82   195.4   858.1     205  861.06
   214.6  864.38   224.2  868.27
#Mann= 3 , 0 , 0
       0      .1       0    99.5    .045       0   121.6      .1       0
Bank Sta=99.5,121.6
XS Rating Curve= 0 ,0
Exp/Cntr=0.3,0.1

Type RM Length L Ch R = 1 ,4705.3  ,152,164.3,175.2
XS GIS Cut Line= 2
     1681019.875      661726.076     1680795.917      661722.604
#Sta/Elev= 26
       0  860.85     9.7  857.76    19.5  854.65    29.2  850.86      39  845.85
    48.7  841.68    58.4  841.13    68.2  842.13    77.9  842.48    87.6  841.94
    97.4   841.2   107.1  840.72   116.9  840.46   126.6  840.12   136.3   839.4
   140.1  839.14   146.1  838.73   155.1  839.98   155.8  840.08   165.6  844.44
   175.3  850.37     185  856.47   194.8   863.1   204.5  870.93   214.2  880.11
     224  890.08
#Mann= 3 , 0 , 0
       0      .1       0   136.3    .045       0   155.1      .1       0
Bank Sta=136.3,155.1
XS Rating Curve= 0 ,0
Exp/Cntr=0.3,0.1

Type RM Length L Ch R = 1 ,4541    ,173.7,177.9,181.1
XS GIS Cut Line= 3
     1681031.377      661649.166     1680969.528      661597.083
     1680887.063       661549.34
#Sta/Elev= 22
       0  854.08       9  852.12      18  850.53      27   849.6    35.9  849.21
    44.9  848.81    53.9  848.07    62.9  846.73    71.9  845.28    80.9  843.36
    90.4  839.89    99.9     837   102.4  836.74   109.4     836   117.4  836.68
     119  836.81   128.5  841.26     138  852.89   147.6  862.01   157.1  867.91
   166.6     873   176.2  878.22
#Mann= 3 , 0 , 0
       0      .1       0    99.9    .045       0     119      .1       0
Bank Sta=99.9,119
XS Rating Curve= 0 ,0
Exp/Cntr=0.3,0.1

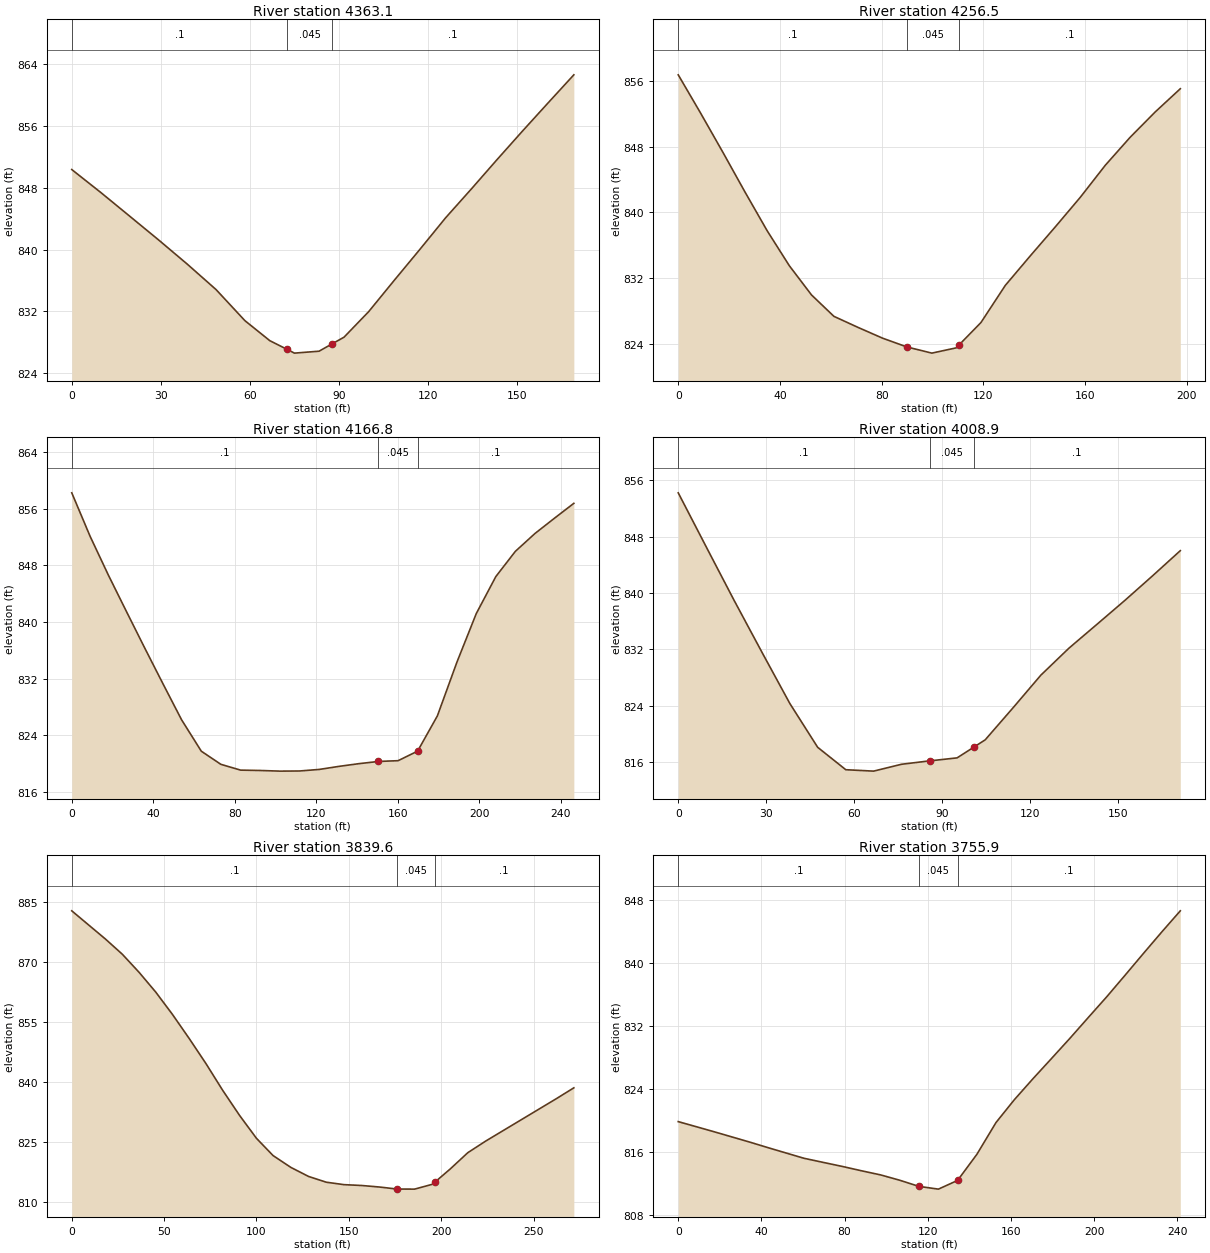
Type RM Length L Ch R = 1 ,4363.1  ,107.8,106.6,104.5
XS GIS Cut Line= 4
     1681100.171      661494.219     1681060.023      661451.901
     1681027.471      661425.859     1680978.643      661377.031
#Sta/Elev= 22
       0  850.33     9.7  847.39    19.4  844.34    29.2  841.25    38.9  838.11
    48.6  834.82    58.3  830.81    66.7  828.22    72.6  827.08      75  826.61
    83.3  826.86    87.6  827.79    91.7  828.67     100  831.97   108.6  836.01
   117.3  840.04   125.9  844.09   134.6  847.83   143.2   851.6   151.8   855.3
   160.4  858.93   169.1  862.57
#Mann= 3 , 0 , 0
       0      .1       0    72.6    .045       0    87.6      .1       0
Bank Sta=72.6,87.6
XS Rating Curve= 0 ,0
Exp/Cntr=0.3,0.1

Type RM Length L Ch R = 1 ,4256.5  ,90.7,89.7,87.9
XS GIS Cut Line= 4
     1681176.125      661429.201     1681141.403      661378.854
     1681085.848      661340.659       1681035.5      661293.784
#Sta/Elev= 24
       0  856.72     8.7  852.12    17.5  847.34    26.2  842.51      35  837.76
    43.7  833.52    52.4  829.98    61.2  827.38    70.8  826.02    80.4  824.72
      90  823.65    95.3  823.25    99.7  822.91   109.3  823.55   110.3  823.87
     119  826.62   128.6  831.14   138.4  834.72   148.2  838.23   158.1  841.85
   167.9  845.73   177.7  849.14   187.5   852.2   197.4  855.03
#Mann= 3 , 0 , 0
       0      .1       0      90    .045       0   110.3      .1       0
Bank Sta=90,110.3
XS Rating Curve= 0 ,0
Exp/Cntr=0.3,0.1

Type RM Length L Ch R = 1 ,4166.8  ,170,157.9,144.4
XS GIS Cut Line= 4
     1681248.391      661364.878     1681213.669      661323.646
     1681106.247      661258.541     1681046.568      661228.159
#Sta/Elev= 29
       0  858.22       9  852.09      18   846.6      27  841.39    35.9  836.29
    44.9  831.22    53.9  826.22    63.6  821.78    73.2  819.93    82.9  819.11
    92.6  819.06   102.2  818.97   111.9  818.99   121.5  819.21   131.2  819.64
   140.9  820.02   150.5  820.33   155.4  820.39   160.2  820.44   169.8  821.79
   170.4   822.1   179.5  826.76   189.1  834.34   198.6  841.19   208.2  846.41
   217.8  849.97   227.4  852.48   236.9  854.62   246.5  856.74
#Mann= 3 , 0 , 0
       0      .1       0   150.5    .045       0   169.8      .1       0
Bank Sta=150.5,169.8
XS Rating Curve= 0 ,0
Exp/Cntr=0.3,0.1

Type RM Length L Ch R = 1 ,4008.9  ,168.9,169.4,168.9
XS GIS Cut Line= 2
     1681293.964      661133.758     1681122.523      661134.844
#Sta/Elev= 21
       0   854.2     9.5  846.58      19  839.01    28.6  831.58    38.1  824.33
    47.6  818.12    57.2  814.94    66.7  814.74    76.2  815.71    85.7  816.19
    85.8  816.19    95.2  816.62   100.8  818.11   104.8  819.18   114.3  823.72
   123.8  828.35   133.4  832.18   142.9  835.54   152.4  838.92   161.9  842.42
   171.4     846
#Mann= 3 , 0 , 0
       0      .1       0    85.8    .045       0   100.8      .1       0
Bank Sta=85.8,100.8
XS Rating Curve= 0 ,0
Exp/Cntr=0.3,0.1

Type RM Length L Ch R = 1 ,3839.6  ,96.5,83.7,70.6
XS GIS Cut Line= 3
     1681372.089      661048.038     1681298.304      660967.743
     1681135.544      660969.913
#Sta/Elev= 27
       0  882.79    18.2  875.74    27.3  871.96    36.4  867.42    45.4  862.49
    54.5  856.87    63.6  850.82    72.7  844.52    81.8   837.8    90.9  831.55
     100  825.85     109  821.53   118.6  818.58   128.2  816.31   137.8  814.87
   147.4  814.26   156.9  814.05   166.5  813.67   176.1  813.16   185.6  813.14
   195.2  814.35   196.4  814.82   204.8  818.15   214.4  822.26     224  825.14
   262.2  835.74   271.8  838.49
#Mann= 3 , 0 , 0
       0      .1       0   176.1    .045       0   196.4      .1       0
Bank Sta=176.1,196.4
XS Rating Curve= 0 ,0
Exp/Cntr=0.3,0.1

Type RM Length L Ch R = 1 ,3755.9  ,244.7,269.8,292.3
XS GIS Cut Line= 4
     1681302.645      660836.449     1681245.136      660854.896
     1681168.096      660905.894      1681089.32      660946.562
#Sta/Elev= 30
       0  819.91     8.6  819.27    17.3  818.62    25.9  817.96    34.5   817.3
    43.1  816.61    51.8  815.93    60.4  815.26    69.6  814.74    78.9  814.22
    88.1  813.67    97.4  813.14   106.6  812.46   115.8  811.68   118.1   811.6
   125.1  811.34   133.1   812.3   134.3  812.44   143.6  815.76   152.8   819.8
   161.6  822.69   170.5  825.34   179.4   827.9   188.2  830.45   197.1  833.11
     206  835.75   214.8  838.48   223.7  841.27   232.6  844.02   241.4  846.67
#Mann= 3 , 0 , 0
       0      .1       0   115.8    .045       0   134.3      .1       0
Bank Sta=115.8,134.3
XS Rating Curve= 0 ,0
Exp/Cntr=0.3,0.1

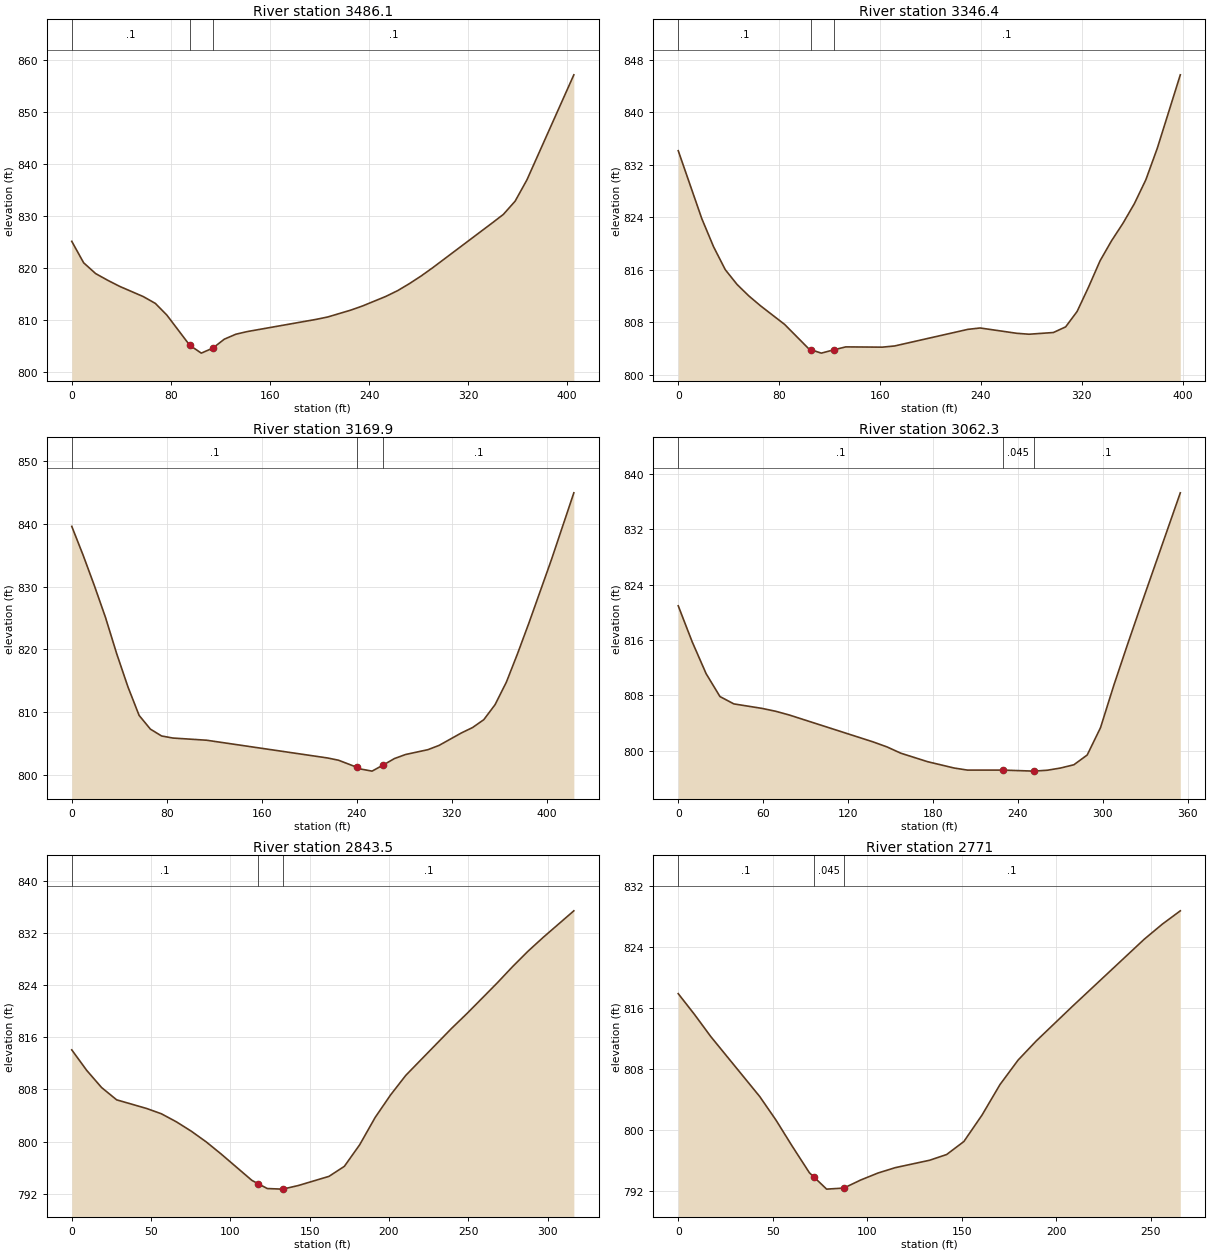
Type RM Length L Ch R = 1 ,3486.1  ,138.5,139.7,140.8
XS GIS Cut Line= 4
     1681342.792      660700.816     1681275.518       660695.39
     1681132.289      660629.201     1680952.167      660625.382
#Sta/Elev= 28
       0  825.17     9.6  821.04    19.3  818.96    28.9  817.69    38.6  816.51
    57.8  814.53    67.5  813.22    76.8  810.97    95.3  805.15   104.6  803.65
   113.9  804.62   123.2  806.34   132.5  807.29   141.7   807.8   197.4  810.15
   206.7  810.61   225.3  811.93   234.8  812.73   253.7  814.58   263.2  815.69
   272.7  817.04   282.2  818.52   291.6  820.12   339.1  828.64   348.5  830.36
     358  832.91   367.5     837   405.4  857.23
#Mann= 3 , 0 , 0
       0      .1       0    95.3    .045       0   113.9      .1       0
Bank Sta=95.3,113.9
XS Rating Curve= 0 ,0
Exp/Cntr=0.3,0.1

Type RM Length L Ch R = 1 ,3346.4  ,187.7,176.5,164.1
XS GIS Cut Line= 4
     1681363.408      660630.286     1681323.261      660567.352
     1681117.098       660459.93     1681041.143      660410.017
#Sta/Elev= 30
       0  834.14    18.7  823.78      28  819.51    37.3  816.01    46.7  813.75
      56  812.01    65.3   810.5    84.3  807.68   103.7  803.92   105.2  803.82
   113.4   803.3   123.1  803.79   132.8  804.25   161.8  804.21   171.5  804.39
   229.6  806.92   239.3  807.13   268.4  806.32   278.1  806.18   297.4  806.44
   307.1   807.3   316.2  809.65   325.3  813.38   334.4  817.37   343.5  820.42
   352.6   823.1   361.6  826.08   370.7  829.72   379.8  834.54     398   845.7
#Mann= 3 , 0 , 0
       0      .1       0   105.2    .045       0   123.1      .1       0
Bank Sta=105.2,123.1
XS Rating Curve= 0 ,0
Exp/Cntr=0.3,0.1

Type RM Length L Ch R = 1 ,3169.9  ,93.5,107.6,125
XS GIS Cut Line= 5
     1681451.968      660474.326     1681371.235      660394.605
      1681260.11      660396.215     1681147.263      660396.215
     1681070.874      660358.368
#Sta/Elev= 30
       0  839.63     9.5  835.06    18.9  830.24    28.4   825.1    37.8  819.33
    47.3  814.02    56.7  809.47    66.2  807.28    75.6  806.19    85.1  805.86
   113.5  805.51   215.3  802.68   224.6  802.32   240.5  801.16   243.4  800.91
   252.8  800.58   262.2  801.55   271.6  802.58     281  803.23   299.8     804
   309.2  804.68     328  806.67   337.4  807.53   346.9  808.79   356.4  811.19
   365.9  814.78   375.3  819.32   384.8  824.17   403.8   834.3   422.7  844.98
#Mann= 3 , 0 , 0
       0      .1       0   240.5    .045       0   262.2      .1       0
Bank Sta=240.5,262.2
XS Rating Curve= 0 ,0
Exp/Cntr=0.3,0.1

Type RM Length L Ch R = 1 ,3062.3  ,205.7,218.8,219.9
XS GIS Cut Line= 3
     1681432.853      660437.144     1681320.006      660327.552
     1681143.139      660239.661
#Sta/Elev= 25
       0  820.95     9.8  815.78    19.7  811.15    29.5  807.84    39.3  806.78
      59  806.14    68.8  805.72    78.6  805.17   137.6   801.3   147.5  800.57
   157.3  799.66   176.1  798.44   194.9  797.52   204.3  797.22   229.2  797.22
   251.4  797.07   260.8   797.2   270.2  797.52   279.6  797.99     289   799.4
   298.4  803.34   307.8  809.46   317.2  815.19   326.6  820.78   354.8  837.27
#Mann= 3 , 0 , 0
       0      .1       0   229.2    .045       0   251.4      .1       0
Bank Sta=229.2,251.4
XS Rating Curve= 0 ,0
Exp/Cntr=0.3,0.1

Type RM Length L Ch R = 1 ,2843.5  ,86.4,72.5,61.9
XS GIS Cut Line= 4
     1681467.575      660343.828     1681408.981      660270.043
     1681359.068      660175.642     1681246.221      660150.686
#Sta/Elev= 30
       0  814.07     9.4  810.93    18.8  808.29    28.3   806.4    47.1  805.08
    56.5  804.26      66  803.02    75.4  801.58    84.8  799.94    94.2  798.08
   113.6  794.03   117.7   793.5   123.3  792.78   132.7  792.69     133  792.69
   142.8  793.24   162.2  794.65   171.9  796.19   181.6  799.52   191.3  803.69
     201  807.14   210.6  810.15   239.5  817.37   249.2  819.65   258.8  822.01
   268.4  824.38     278  826.86   287.7  829.22   297.3  831.35   316.6  835.42
#Mann= 3 , 0 , 0
       0      .1       0   117.7    .045       0     133      .1       0
Bank Sta=117.7,133
XS Rating Curve= 0 ,0
Exp/Cntr=0.3,0.1

Type RM Length L Ch R = 1 ,2771    ,94.5,84.7,75.8
XS GIS Cut Line= 4
     1681512.714      660248.139     1681464.971      660211.247
     1681382.506      660173.269     1681271.829      660143.973
#Sta/Elev= 24
       0  817.87     8.6  815.15    17.2  812.26    43.1  804.41    51.7  801.33
    60.3  797.91    69.4  794.43    71.8  793.87    78.5  792.29    87.6  792.43
    96.6  793.49   105.7   794.4   114.8   795.1     133  796.07     142  796.82
   151.1  798.52   160.7  801.98   170.2  805.97   179.8  809.18   189.3  811.66
   208.4  816.18   246.5  824.99   256.1  826.97   265.6  828.71
#Mann= 3 , 0 , 0
       0      .1       0    71.8    .045       0    87.6      .1       0
Bank Sta=71.8,87.6
XS Rating Curve= 0 ,0
Exp/Cntr=0.3,0.1

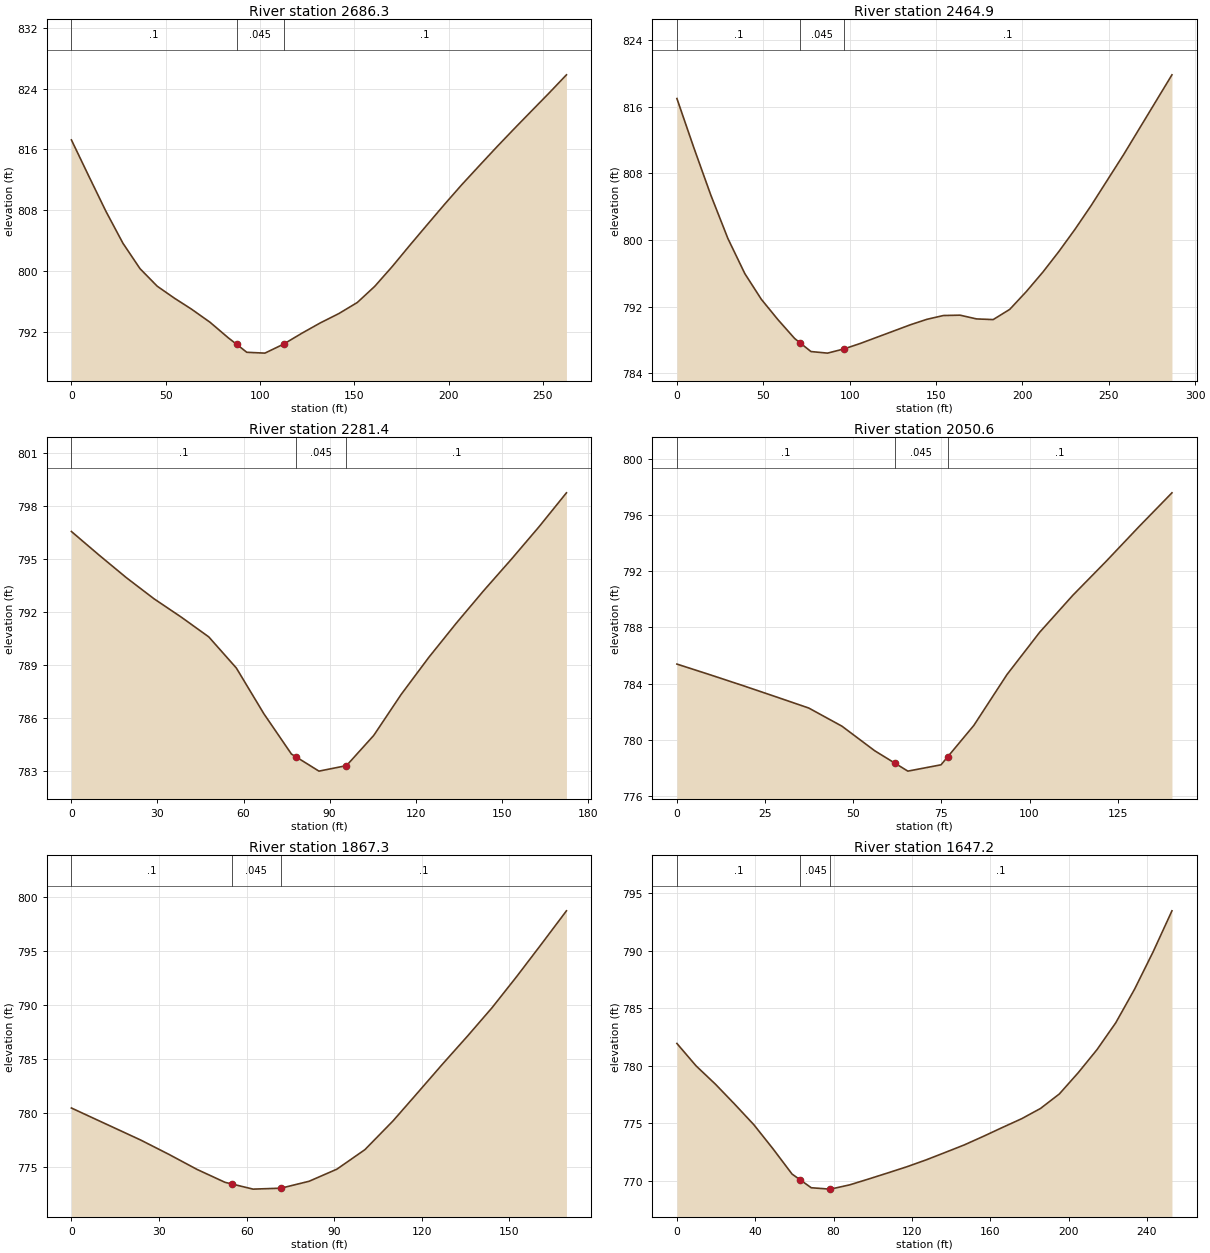
Type RM Length L Ch R = 1 ,2686.3  ,221.6,221.4,219.5
XS GIS Cut Line= 4
     1681531.594      660137.665     1681469.745      660122.474
     1681381.855      660120.304     1681271.178      660126.814
#Sta/Elev= 30
       0  817.24     9.1  812.54    18.2   807.9    27.3  803.66    36.4   800.3
    45.5     798    54.6  796.43    63.7  794.98    73.5  793.26    83.2  791.21
    87.6  790.36      93  789.31   102.6   789.2   112.5  790.38   122.3  791.83
   132.1  793.19   141.8   794.4   151.6  795.86   160.8  797.97   170.1  800.58
   179.3  803.34   188.6  806.07   197.8  808.75     207  811.35   216.3  813.85
   225.5   816.3   234.8  818.71     244  821.05   253.2  823.38   262.5   825.8
#Mann= 3 , 0 , 0
       0      .1       0    87.6    .045       0   112.5      .1       0
Bank Sta=87.6,112.5
XS Rating Curve= 0 ,0
Exp/Cntr=0.3,0.1

Type RM Length L Ch R = 1 ,2464.9  ,182.9,183.4,183.7
XS GIS Cut Line= 4
     1681570.657      659954.288     1681531.594      659949.948
     1681359.068      659947.778     1681285.283      659959.713
#Sta/Elev= 27
       0  816.99     9.8  811.08    19.6   805.4    29.5  800.18    39.3  795.96
    48.9  792.86    58.5  790.42    68.1  788.17    71.4  787.62    77.6  786.59
    87.2   786.4    96.8  786.91   106.4  787.58   135.2  789.81   144.7  790.46
   154.3  790.92   163.9  790.96   173.5  790.51   183.1  790.43   192.7  791.66
   202.3   793.8   211.8  796.12   221.2  798.63   230.5  801.29   239.9  804.16
   258.6  810.25   286.6  819.84
#Mann= 3 , 0 , 0
       0      .1       0    71.4    .045       0    96.8      .1       0
Bank Sta=71.4,96.8
XS Rating Curve= 0 ,0
Exp/Cntr=0.3,0.1

Type RM Length L Ch R = 1 ,2281.4  ,240.7,230.8,219
XS GIS Cut Line= 2
     1681528.339      659783.932     1681355.813      659780.677
#Sta/Elev= 21
       0  796.56     9.6  795.23    19.2  793.94    28.8  792.75    38.4   791.7
    47.9  790.59    57.5  788.83    67.1  786.24    76.7  783.96    78.4  783.79
    86.3  782.99    93.4  783.22    95.9   783.3   105.4  785.01     115  787.34
   124.6  789.43   134.2  791.37   143.8  793.22   153.4  794.99     163  796.82
   172.6  798.75
#Mann= 3 , 0 , 0
       0      .1       0    78.4    .045       0    95.9      .1       0
Bank Sta=78.4,95.9
XS Rating Curve= 0 ,0
Exp/Cntr=0.3,0.1

Type RM Length L Ch R = 1 ,2050.6  ,181.8,183.3,185
XS GIS Cut Line= 2
      1681457.81      659532.196     1681329.771      659589.705
#Sta/Elev= 18
       0  785.39     9.4  784.63    18.7  783.86    28.1  783.06    37.4  782.26
    46.8  780.97    56.1  779.22    61.8  778.34    65.5  777.77    74.9  778.22
    76.8  778.79    84.2  781.02    93.6  784.64   102.9  787.66   112.3  790.29
   121.6  792.67     131  795.16   140.4  797.58
#Mann= 3 , 0 , 0
       0      .1       0    61.8    .045       0    76.8      .1       0
Bank Sta=61.8,76.8
XS Rating Curve= 0 ,0
Exp/Cntr=0.3,0.1

Type RM Length L Ch R = 1 ,1867.3  ,219.8,220.1,217.4
XS GIS Cut Line= 4
     1681414.407       659368.35     1681392.705      659378.116
     1681309.155      659399.817     1681252.731      659418.264
#Sta/Elev= 22
       0  780.47     7.9  779.48    15.9  778.48    23.8  777.49    33.4  776.17
      43  774.78    52.6  773.58    54.9  773.43    62.2  772.95    69.9  773.02
    71.8  773.04    81.4  773.68    90.9   774.8   100.5  776.61   110.1  779.27
   118.6   781.9   127.1  784.55   135.6  787.13     144  789.76   152.5  792.67
     161  795.69   169.5  798.75
#Mann= 3 , 0 , 0
       0      .1       0    54.9    .045       0    71.8      .1       0
Bank Sta=54.9,71.8
XS Rating Curve= 0 ,0
Exp/Cntr=0.3,0.1

Type RM Length L Ch R = 1 ,1647.2  ,193.7,191.4,188.6
XS GIS Cut Line= 4
     1681372.089      659171.953     1681333.027      659176.293
     1681206.073      659227.291      1681151.82      659281.545
#Sta/Elev= 29
       0  781.92     9.8  779.97    19.6  778.39    29.5  776.64    39.3  774.85
    49.1  772.75    58.8  770.56    63.1  770.04    68.6  769.37    78.1  769.25
    78.4  769.25    88.2  769.62    97.9  770.13   107.7  770.66   117.5   771.2
   127.2  771.79     137  772.44   146.8   773.1   156.6  773.85   166.3  774.62
   176.1  775.38   185.7  776.27   195.3  777.53   204.9  779.37   214.5  781.38
   224.1  783.72   233.7  786.64   243.2   789.9   252.8  793.46
#Mann= 3 , 0 , 0
       0      .1       0    63.1    .045       0    78.4      .1       0
Bank Sta=63.1,78.4
XS Rating Curve= 0 ,0
Exp/Cntr=0.3,0.1

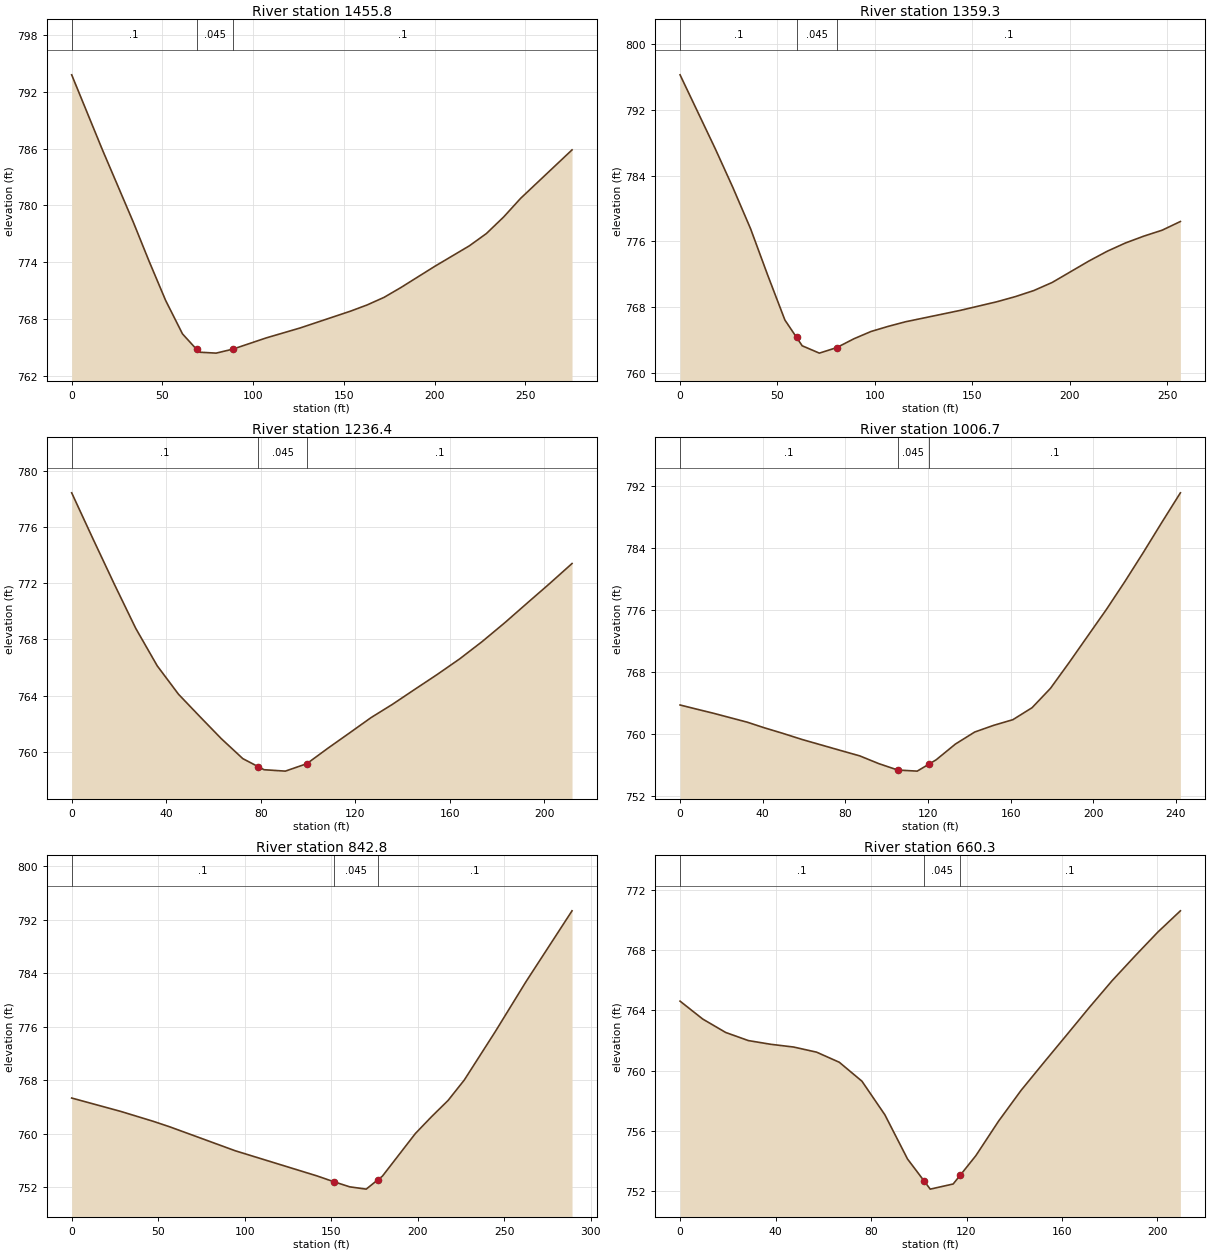
Type RM Length L Ch R = 1 ,1455.8  ,97.4,96.5,95.9
XS GIS Cut Line= 4
     1681274.433       658970.13     1681248.391      659003.767
     1681126.863      659071.041     1681051.994       659128.55
#Sta/Elev= 22
       0  793.82      17  785.86      34  778.22    42.5  774.18    51.8  769.95
    61.1  766.41    68.9  764.77    70.3  764.48    79.6  764.38    88.8   764.8
   107.4     766   125.9  767.04   153.7  768.82   162.9  769.48   172.2  770.28
   181.4  771.31   200.3  773.58   219.2  775.73   228.6  777.03   238.1  778.78
   247.5  780.76   275.8  785.88
#Mann= 3 , 0 , 0
       0      .1       0    68.9    .045       0    88.8      .1       0
Bank Sta=68.9,88.8
XS Rating Curve= 0 ,0
Exp/Cntr=0.3,0.1

Type RM Length L Ch R = 1 ,1359.3  ,121.9,122.8,122.6
XS GIS Cut Line= 4
     1681220.396      658908.715     1681189.146      658926.944
     1681121.438      658968.611     1680999.042      659038.923
#Sta/Elev= 25
       0  796.25    18.1  787.25    27.1  782.56    36.2  777.54      45  771.89
    53.8  766.45    59.8  764.33    62.7  763.31    71.5  762.42    80.4  763.09
    89.2  764.16      98  765.05   106.8  765.67   115.7  766.23   143.9  767.62
   162.7  768.67   172.1  769.29   181.6  770.03     191  771.01   209.8  773.61
   219.2   774.8   228.6  775.81     238  776.64   247.4  777.36   256.8  778.42
#Mann= 3 , 0 , 0
       0      .1       0    59.8    .045       0    80.4      .1       0
Bank Sta=59.8,80.4
XS Rating Curve= 0 ,0
Exp/Cntr=0.3,0.1

Type RM Length L Ch R = 1 ,1236.4  ,235.8,229.7,219.2
XS GIS Cut Line= 4
     1681140.969      658829.071     1681101.907      658851.857
     1681023.782       658897.43     1680968.443      658949.514
#Sta/Elev= 26
       0  778.43       9  775.16    18.1  771.91    27.1  768.79    36.2  766.12
    45.2   764.1    54.3   762.5    63.3  760.94    72.4  759.52      79  758.94
    81.4  758.73    90.4  758.63      94  758.84    99.5  759.16   108.5  760.27
   117.6  761.35   126.6  762.43   135.7  763.38   145.2  764.45   154.7  765.51
   164.2  766.62   173.7  767.85   183.2  769.18   192.7  770.58   202.2  771.97
   211.7   773.4
#Mann= 3 , 0 , 0
       0      .1       0      79    .045       0    99.5      .1       0
Bank Sta=79,99.5
XS Rating Curve= 0 ,0
Exp/Cntr=0.3,0.1

Type RM Length L Ch R = 1 ,1006.7  ,141.9,163.9,183.2
XS GIS Cut Line= 4
     1681044.398      658663.055     1681010.761      658685.842
     1680921.785      658780.243     1680858.851      658814.965
#Sta/Elev= 29
       0  763.73     8.1  763.19    16.2  762.66    24.4  762.08    32.5  761.51
    40.6   760.8    49.9  760.05    59.2  759.26    68.4  758.56    77.7  757.85
      87  757.15    96.2  756.15   105.4  755.32   114.8  755.18   120.4  756.07
     124  756.65   133.3  758.68   142.6  760.23   151.8   761.1   161.1  761.83
   170.4  763.38   179.3  765.88   188.3   769.2   197.3  772.63   206.3  776.05
   215.3  779.68   224.3  783.47   233.2  787.33   242.2  791.16
#Mann= 3 , 0 , 0
       0      .1       0   105.4    .045       0   120.4      .1       0
Bank Sta=105.4,120.4
XS Rating Curve= 0 ,0
Exp/Cntr=0.3,0.1

Type RM Length L Ch R = 1 ,842.8   ,184.1,182.5,181.4
XS GIS Cut Line= 3
     1681061.759      658601.206      1680834.98      658590.356
     1680777.471      658614.227
#Sta/Elev= 18
       0  765.33    28.4  763.33    47.3  761.84    56.8  761.02    94.6  757.45
   141.9  753.69   151.4  752.84   160.8  752.06   170.3  751.72   176.9  753.09
   179.7  753.67   198.7  760.02   208.1  762.55   217.6  764.96     227  768.02
   244.8   775.2   262.6  782.68   289.3   793.3
#Mann= 3 , 0 , 0
       0      .1       0   151.4    .045       0   176.9      .1       0
Bank Sta=151.4,176.9
XS Rating Curve= 0 ,0
Exp/Cntr=0.3,0.1

Type RM Length L Ch R = 1 ,660.3   ,147.5,147.8,148.1
XS GIS Cut Line= 2
     1681020.223      658412.274     1680810.587      658412.274
#Sta/Elev= 25
       0  764.62     9.5  763.43    19.1  762.54    28.6     762    38.1  761.75
    47.6  761.57    57.2  761.23    66.7  760.56    76.2   759.3    85.8  757.07
    95.3  754.13   102.3  752.66   104.8  752.13   114.4  752.47   117.3  753.04
   123.9  754.35   133.4  756.64   142.9   758.7   152.5  760.56     162  762.38
   171.5  764.21     181  765.98   190.6  767.62   200.1   769.2   209.6  770.62
#Mann= 3 , 0 , 0
       0      .1       0   102.3    .045       0   117.3      .1       0
Bank Sta=102.3,117.3
XS Rating Curve= 0 ,0
Exp/Cntr=0.3,0.1

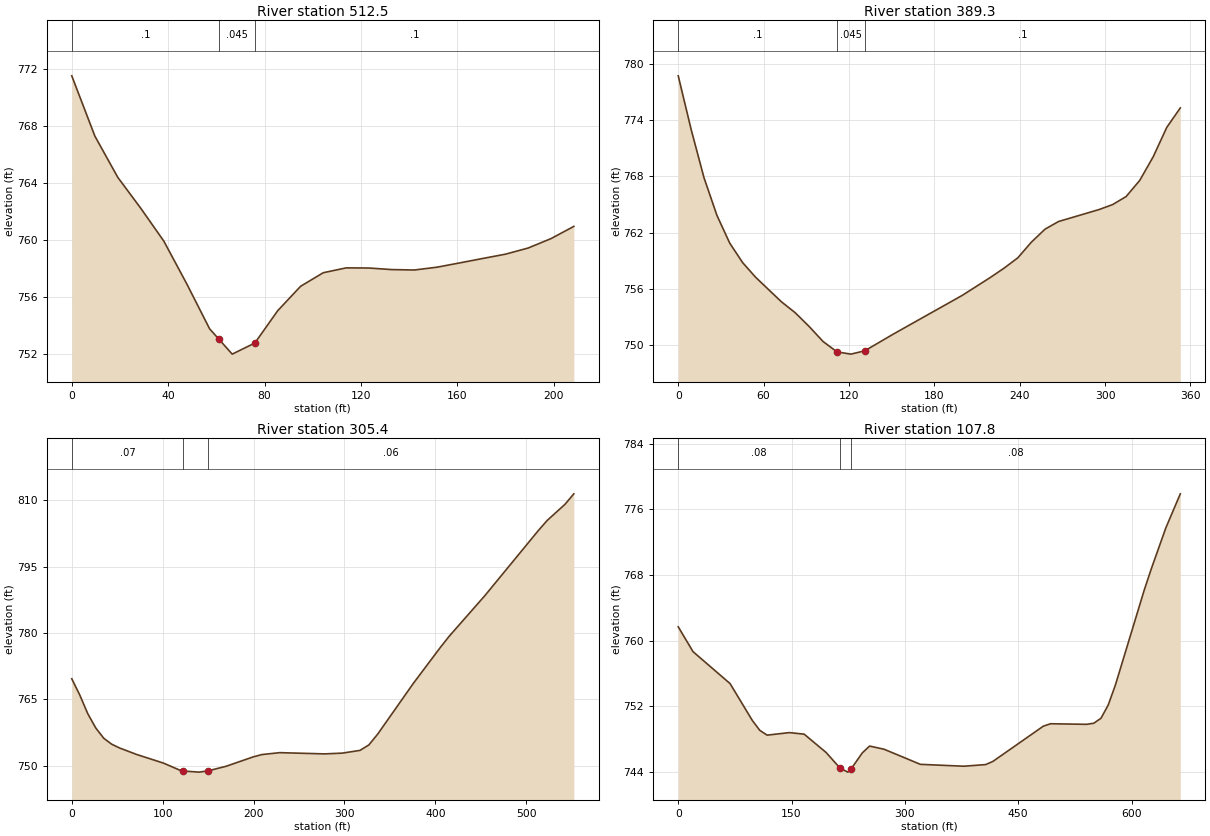
Type RM Length L Ch R = 1 ,512.5   ,127.6,123.2,116.8
XS GIS Cut Line= 3
     1681011.846      658269.175     1680964.103      658269.175
     1680803.513      658267.005
#Sta/Elev= 24
       0  771.49     9.6  767.26    19.1  764.37    28.6  762.21    38.2   759.9
    47.7  756.91    57.2  753.75      61  753.03    66.6  751.97      76  752.75
    85.5  755.02      95  756.73   104.4  757.68   113.9  758.02   123.3  758.01
   132.8   757.9   142.2  757.87   151.7  758.07   161.1  758.37   170.6  758.68
     180  758.98   189.4  759.41   198.9  760.07   208.4  760.93
#Mann= 3 , 0 , 0
       0      .1       0      61    .045       0      76      .1       0
Bank Sta=61,76
XS Rating Curve= 0 ,0
Exp/Cntr=0.3,0.1

Type RM Length L Ch R = 1 ,389.3   ,70.9,83.9,96.9
XS GIS Cut Line= 4
     1680988.973      658189.618     1680919.962      658167.482
     1680757.202      658201.337     1680677.775      658283.368
#Sta/Elev= 29
       0  778.76     9.1  773.01    18.1  767.87    27.2  763.84    36.2  760.87
    45.3  758.78    54.4  757.22    72.5   754.6    82.2  753.43      92  751.96
   101.8  750.35   111.6  749.24   121.4     749   131.2  749.36   150.7   751.1
   199.6  755.28   219.2  757.18   228.9  758.18   238.7   759.3   248.2  760.97
   257.8  762.36   267.3  763.18   295.8  764.46   305.3  764.99   314.8  765.85
   324.4  767.58   333.9  770.12   343.4  773.25   352.9  775.33
#Mann= 3 , 0 , 0
       0      .1       0   111.6    .045       0   131.2      .1       0
Bank Sta=111.6,131.2
XS Rating Curve= 0 ,0
Exp/Cntr=0.3,0.1

Type RM Length L Ch R = 1 ,305.4   ,193.2,197.6,200.8
XS GIS Cut Line= 4
     1680982.549      658159.583     1680936.343      658118.857
     1680789.208      658062.867     1680465.188      657984.236
#Sta/Elev= 30
       0  769.68     8.8  766.02    17.6   761.8    26.4  758.57    35.2  756.24
      44  754.89    52.8  754.03    71.4  752.58     101  750.62   120.6  748.88
   122.6  748.84   140.3  748.59   150.2  748.89   169.8  749.91   199.3  752.01
   209.2  752.56   228.8  752.99   277.9  752.71   297.5  752.88   317.1   753.5
   326.9  754.74   336.7  757.21   375.9  768.67   405.4  776.73   415.2  779.28
   454.4  788.44   513.2  803.14     523  805.44   542.6  809.09   552.4  811.47
#Mann= 3 , 0 , 0
       0     .07       0   122.6    .045       0   150.2     .06       0
Bank Sta=122.6,150.2
XS Rating Curve= 0 ,0
Exp/Cntr=0.3,0.1

Type RM Length L Ch R = 1 ,107.8   ,111,107.8,103.9
XS GIS Cut Line= 4
     1681045.483      658098.819     1680977.124      657936.059
     1680776.952        657822.1     1680519.875      657804.548
#Sta/Elev= 30
       0  761.69    19.6  758.66    68.6  754.77    98.1  750.27   107.9  749.07
   117.7  748.48   147.1  748.79   166.7   748.6   195.7  746.37   214.2  744.46
   224.5  743.97   229.2  744.41   243.7  746.32   253.3  747.15   272.5  746.76
   320.5  744.92   378.1  744.69   406.9  744.89   416.4  745.27   483.2  749.57
   492.8  749.87   540.5   749.8     550  749.93   559.6  750.54   569.1  752.14
   578.6  754.57   616.8  766.16   626.4  768.82   645.5  773.77   664.6  777.91
#Mann= 3 , 0 , 0
       0     .08       0   214.2    .045       0   229.2     .08       0
Bank Sta=214.2,229.2
XS Rating Curve= 0 ,0
Exp/Cntr=0.3,0.1

Chan Stop Cuts=-1
Use User Specified Reach Order=0
Composite Channel Slope=5